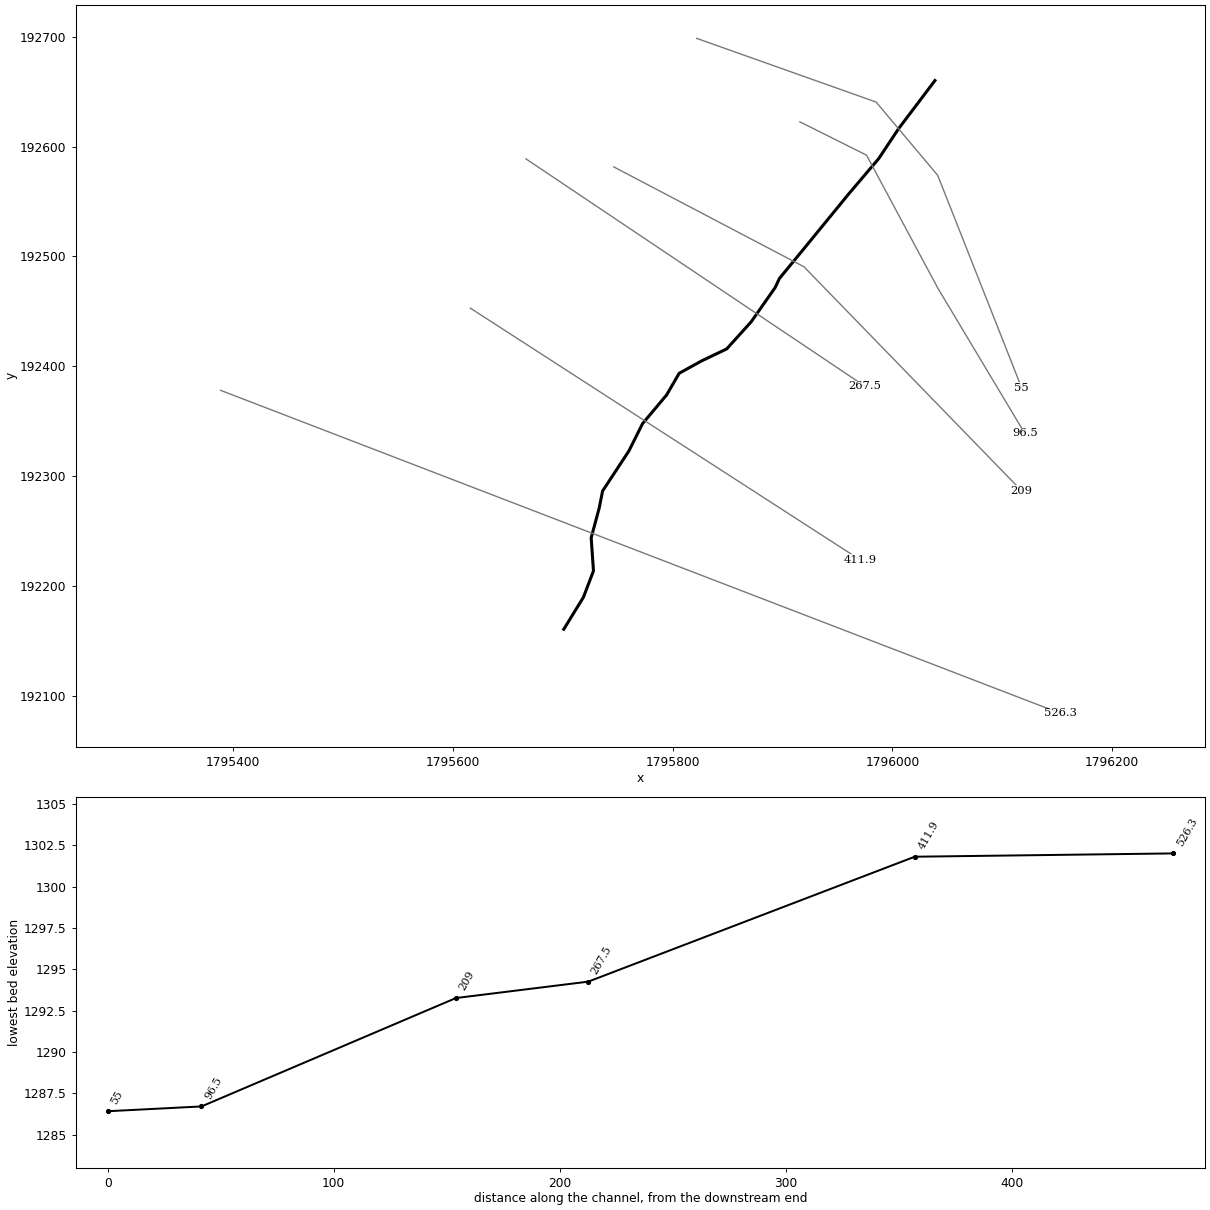
--- TrkywllwBr.prj (project) ---

Proj Title=TrkywllwBr
Current Plan=p01
Geom File=g01
Flow File=f01
Plan File=p01
DSS Export Rating Curves=0
DSS Export Rating Curve Sorted=0
DSS Export Volume Flow Curves=0
DXF OffsetX=0
DXF OffsetY=0
DXF ScaleX=0
DXF ScaleY=0

--- TrkywllwBr.p01 (plan) ---

Plan Title=Floodplain
Program Version=4.00
Geom File=g01
Flow File=f01
K Sum by GR=0
Std Step Tol=0.01
Critical Tol=0.01
Num of Std Step Trials=20
Max Error Tol=0.3
Flow Tol Ratio=0.001
Split Flow NTrial=30
Split Flow Tol=0.02
Split Flow Ratio=0.02
Log Output Level=0
Friction Slope Method=1
Unsteady Friction Slope Method=2
Unsteady Bridges Friction Slope Method=1
Global Log Level=0
CheckData=False
Run HTab=0
Run UNet=0
Run PostProcess=0
UNET Theta=0
UNET Theta Warmup=0
UNET ZTol=0
UNET ZSATol=0
UNET MxIter=0
UNET MaxInSteps=0
UNET DtIC=0
UNET DtMin=0
UNET MaxCRTS=0
UNET WFStab=0
UNET SFStab=0
UNET WFX=0
UNET SFX=0
UNET DSS MLevel=0
UNET DZMax Abort=0
UNET Convert EG Bridges=0
UNET Use Existing IB Tables=0
UNET Froude Limit=0
UNET Froude Power=0
Write IC File=0
Echo Input=False
Echo Output=False
Write Detailed=0

--- TrkywllwBr.f01 (steady flow) ---

Flow Title=NFF Regression Equation
Program Version=4.00
Number of Profiles=1
Profile Names=P100yr
River Rch & RM=TrkywllwBr,Main      ,526.3
559.0161
River Rch & RM=TrkywllwBr,Main      ,526.3
357.6627
River Rch & RM=TrkywllwBr,Main      ,209
561.0642
River Rch & RM=TrkywllwBr,Main      ,209
357.6627
Boundary for River Rch & Prof#=TrkywllwBr,Main      ,1
Up Type=0
Dn Type=3
Dn Slope=0.027322

--- TrkywllwBr.g01 (geometry) ---

Geom Title=USGS 10m DEM
Program Version=4.00

River Reach=TrkywllwBr     ,Main
Reach XY= 21
     1795700.888      192160.742     1795718.739      192189.750
     1795727.927      192213.781     1795725.847      192243.940
     1795733.127      192270.979     1795736.247      192286.578
     1795760.166      192322.978     1795772.646      192347.937
     1795794.485      192373.936     1795805.925      192393.696
     1795826.724      192405.135     1795849.226      192415.897
     1795849.807      192416.541     1795871.443      192440.494
     1795893.283      192471.694     1795897.201      192480.020
     1795918.031      192505.343     1795960.680      192557.469
     1795987.533      192589.061     1796005.599      192616.249
     1796038.746      192660.150

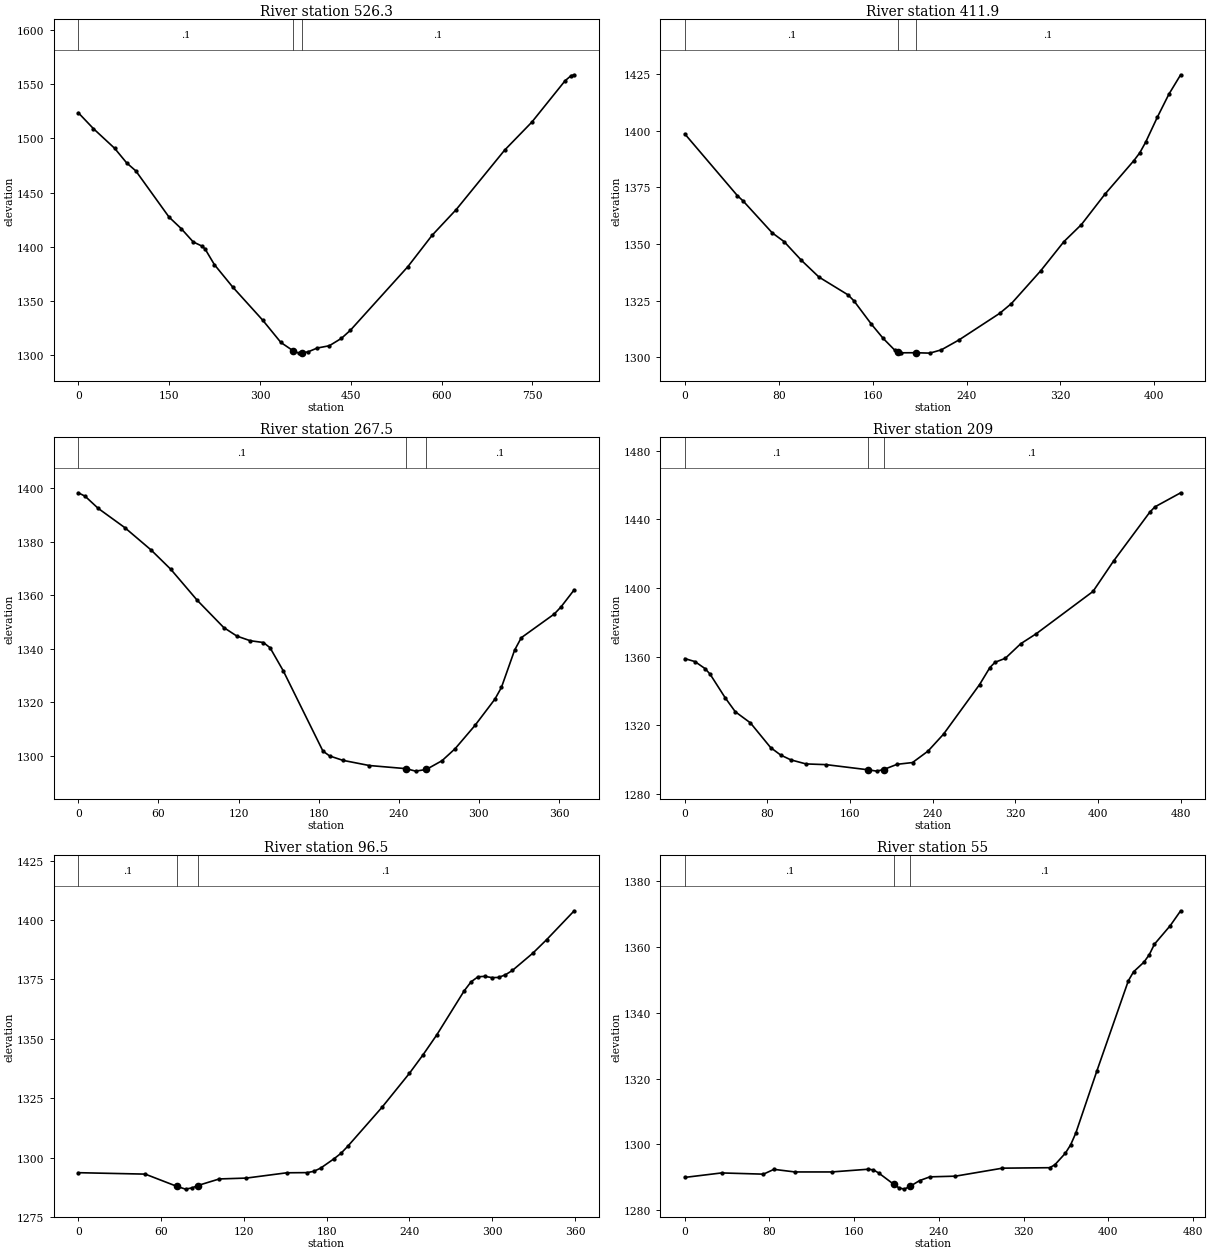
Type RM Length L Ch R = 1 ,526.3,119.1,114.4,109.8
XS GIS Cut Line= 3
     1795388.568      192378.148     1795770.771      192231.143
     1796152.975      192084.137
#Sta/Elev= 30
       0 1523.65    25.0 1508.97    59.9 1490.92    79.9 1477.38    94.9 1470.09
   149.8 1427.48   169.8 1416.90   189.8 1404.53   204.8 1400.55   209.7 1397.74
   224.7 1383.65   254.7 1363.14   304.6 1332.36   334.6 1311.81     355 1304.09
   364.6 1302.00     370 1302.28   379.5 1303.17   394.5 1306.68   414.5 1308.79
   434.5 1315.59   449.4 1323.10   544.3 1381.74   584.3 1410.62   624.2 1434.40
   704.1 1489.16   749.1 1515.03   804.0 1553.17   814.0 1557.88   819.0 1558.64
#Mann= 3 , 0 , 0
       0     0.1       0     355   0.045       0     370     0.1       0
Bank Sta=     355,     370
Exp/Cntr=0.3,0.1

Type RM Length L Ch R = 1 ,411.9,145,144.4,143.8
XS GIS Cut Line= 2
     1795615.862      192452.984     1795970.694      192223.842
#Sta/Elev= 30
       0 1398.64    44.7 1371.43    49.7 1369.01    74.5 1354.92    84.5 1351.10
    99.4 1342.77   114.3 1335.40   139.1 1327.52   144.1 1324.89   159.0 1314.56
   169.0 1308.31   178.9 1303.09   181.6 1302.46   183.9 1301.94   196.6 1301.98
   208.7 1301.80   218.6 1303.26   233.6 1307.63   268.3 1319.39   278.3 1323.72
   303.1 1338.11   323.0 1351.07   337.9 1358.60   357.8 1371.94   382.6 1386.86
   387.6 1390.29   392.6 1394.98   402.5 1405.95   412.4 1416.19   422.4 1424.74
#Mann= 3 , 0 , 0
       0     0.1       0   181.6   0.045       0   196.6     0.1       0
Bank Sta=   181.6,   196.6
Exp/Cntr=0.3,0.1

Type RM Length L Ch R = 1 ,267.5,56,58.5,57.1
XS GIS Cut Line= 2
     1795666.471      192588.861     1795974.895      192381.956
#Sta/Elev= 30
       0 1398.30     5.0 1397.06    14.9 1392.48    34.7 1385.33    54.5 1376.93
    69.3 1369.69    89.1 1358.10   108.9 1347.94   118.8 1344.73   128.8 1343.00
   138.6 1342.34   143.6 1340.39   153.5 1331.76   183.2 1301.76   188.2 1299.93
   198.1 1298.29   217.9 1296.35   245.6 1295.17   252.6 1294.25   260.6 1294.86
   272.4 1298.14   282.3 1302.67   297.1 1311.33   312.0 1321.14   316.9 1325.52
   326.8 1339.50   331.8 1344.13   356.5 1352.99   361.5 1355.62   371.4 1362.02
#Mann= 3 , 0 , 0
       0     0.1       0   245.6   0.045       0   260.6     0.1       0
Bank Sta=   245.6,   260.6
Exp/Cntr=0.3,0.1

Type RM Length L Ch R = 1 ,209,118.7,112.5,102.5
XS GIS Cut Line= 3
     1795746.386      192581.575     1795919.452      192490.691
     1796117.655      192286.687
#Sta/Elev= 30
       0 1358.86     9.8 1357.13    19.6 1353.04    24.4 1349.86    39.1 1336.01
    48.9 1327.86    63.5 1321.39    83.1 1306.97    92.8 1302.64   102.6 1299.83
   117.3 1297.46   136.8 1297.04   177.4 1294.04   185.7 1293.26   192.4 1294.17
   205.5 1297.24   220.4 1298.26   235.4 1304.93   250.4 1314.80   285.3 1343.72
   295.3 1353.66   300.3 1356.73   310.2 1359.03   325.2 1367.56   340.2 1373.38
   395.1 1398.02   415.0 1415.76   450.0 1444.18   455.0 1447.32   479.9 1455.51
#Mann= 3 , 0 , 0
       0     0.1       0   177.4   0.045       0   192.4     0.1       0
Bank Sta=   177.4,   192.4
Exp/Cntr=0.3,0.1

Type RM Length L Ch R = 1 ,96.5,44.2,41.5,46.4
XS GIS Cut Line= 4
     1795915.778      192622.569     1795976.495      192592.210
     1796041.274      192471.354     1796120.556      192338.896
#Sta/Elev= 30
       0 1293.63    48.5 1293.03    71.6 1287.84    77.7 1286.71    82.6 1287.26
    86.6 1288.23   102.2 1291.00   121.8 1291.36   151.1 1293.59   165.8 1293.66
   170.7 1294.21   175.6 1295.54   185.4 1299.52   190.3 1301.75   195.2 1304.69
   220.0 1321.09   239.9 1335.41   249.8 1343.22   259.8 1351.64   279.7 1370.22
   284.7 1374.01   289.7 1376.12   294.6 1376.32   299.6 1375.79   304.6 1375.84
   309.6 1376.98   314.6 1378.78   329.5 1386.10   339.5 1391.79   359.4 1403.90
#Mann= 3 , 0 , 0
       0     0.1       0    71.6   0.045       0    86.6     0.1       0
Bank Sta=    71.6,    86.6
Exp/Cntr=0.3,0.1

Type RM Length L Ch R = 1 ,55,49.8,55,60.2
XS GIS Cut Line= 4
     1795821.800      192698.563     1795985.197      192640.552
     1796041.274      192573.840     1796117.655      192380.471
#Sta/Elev= 30
       0 1289.98    34.7 1291.34    74.3 1290.97    84.2 1292.43   104.0 1291.64
   138.7 1291.64   173.4 1292.47   178.2 1292.26   183.1 1291.34   197.6 1287.84
   202.4 1286.79   207.3 1286.42   212.6 1287.23   221.8 1289.01   231.5 1290.15
   255.7 1290.36   300.1 1292.79   344.7 1292.93   349.6 1293.82   359.5 1297.33
   364.5 1299.88   369.4 1303.47   389.2 1322.25   419.0 1349.72   423.9 1352.44
   433.8 1355.40   438.8 1357.67   443.7 1360.86   458.6 1366.48   468.4 1370.98
#Mann= 3 , 0 , 0
       0     0.1       0   197.6   0.045       0   212.6     0.1       0
Bank Sta=   197.6,   212.6
Exp/Cntr=0.3,0.1